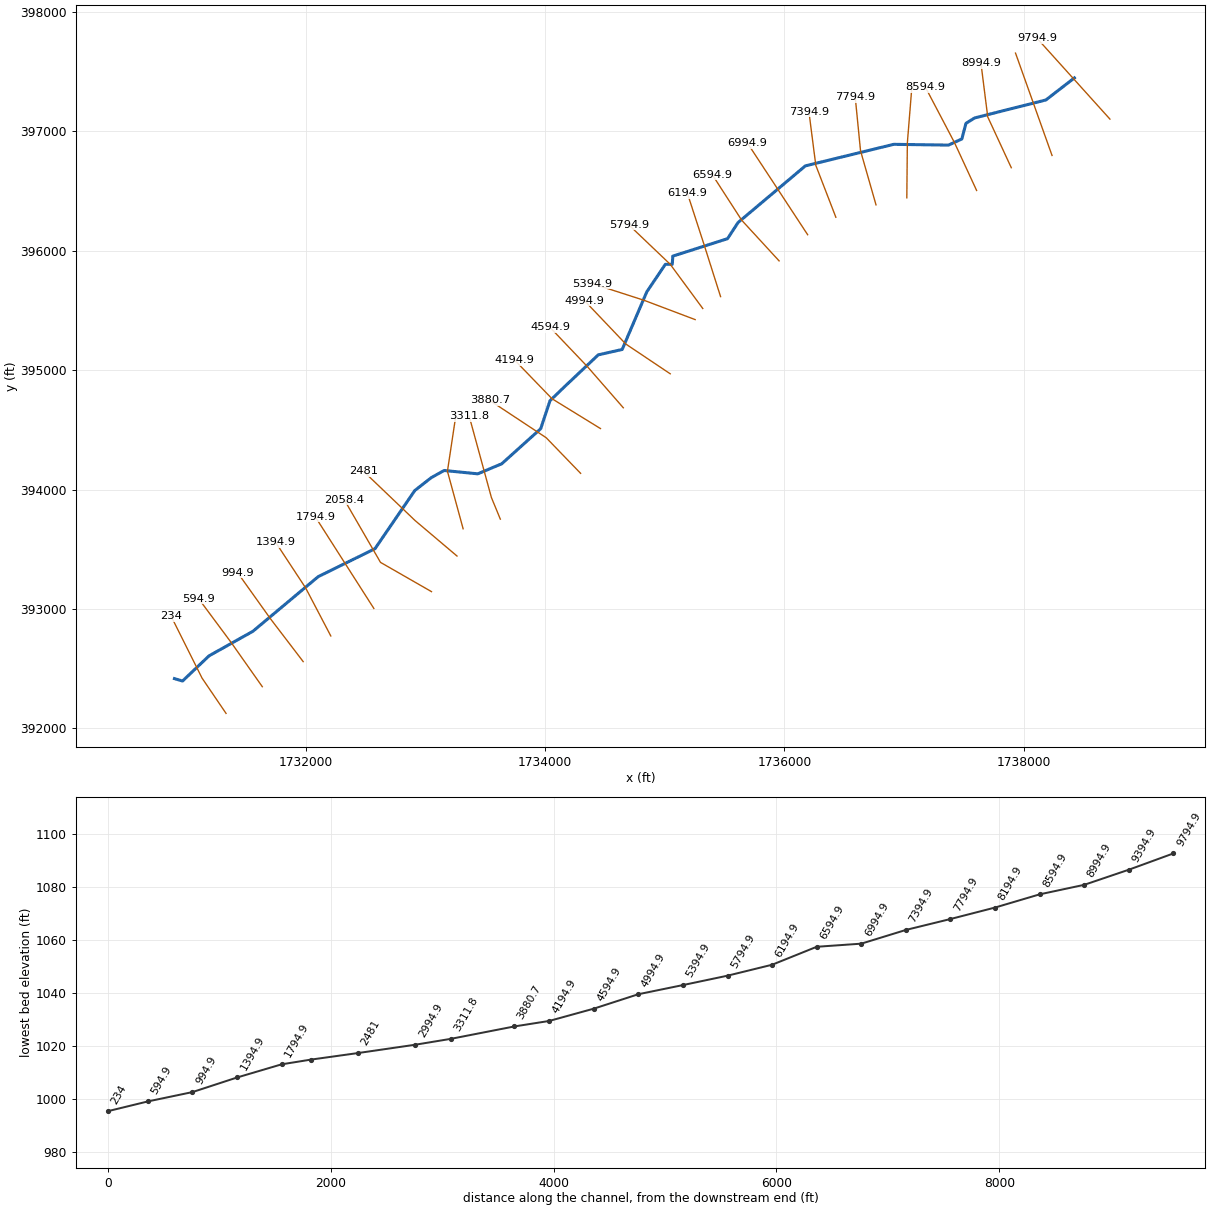
--- DdlyFrk.prj (project) ---

Proj Title=DdlyFrk
Current Plan=p01
Default Exp/Contr=0,0
English Units
Geom File=g01
Flow File=f01
Plan File=p01
BEGIN DESCRIPTION:
END DESCRIPTION:
DSS Export Rating Curves= 0
DSS Export Rating Curve Sorted= 0
DSS Export Volume Flow Curves= 0
DXF OffsetX= 0
DXF OffsetY= 0
DXF ScaleX= 0
DXF ScaleY= 0

--- DdlyFrk.p01 (plan) ---

Plan Title=Floodplain
Program Version=4.00
Geom File=g01
Flow File=f01
K Sum by GR=0
Std Step Tol=0.01
Critical Tol=0.01
Num of Std Step Trials=20
Max Error Tol=0.3
Flow Tol Ratio=0.001
Split Flow NTrial=30
Split Flow Tol=0.02
Split Flow Ratio=0.02
Log Output Level=0
Friction Slope Method=1
Unsteady Friction Slope Method=2
Unsteady Bridges Friction Slope Method=1
Global Log Level=0
CheckData=False
Run HTab=0
Run UNet=0
Run PostProcess=0
UNET Theta=0
UNET Theta Warmup=0
UNET ZTol=0
UNET ZSATol=0
UNET MxIter=0
UNET MaxInSteps=0
UNET DtIC=0
UNET DtMin=0
UNET MaxCRTS=0
UNET WFStab=0
UNET SFStab=0
UNET WFX=0
UNET SFX=0
UNET DSS MLevel=0
UNET DZMax Abort=0
UNET Convert EG Bridges=0
UNET Use Existing IB Tables=0
UNET Froude Limit=0
UNET Froude Power=0
Write IC File=0
Echo Input=False
Echo Output=False
Write Detailed=0

--- DdlyFrk.f01 (steady flow) ---

Flow Title=NFF Regression Equation
Program Version=4.00
Number of Profiles=1
Profile Names=P100yr
River Rch & RM=DdlyFrk,Main      ,9794.9
691.5380
River Rch & RM=DdlyFrk,Main      ,9394.9
747.4272
River Rch & RM=DdlyFrk,Main      ,8594.9
788.5428
River Rch & RM=DdlyFrk,Main      ,7794.9
859.0876
River Rch & RM=DdlyFrk,Main      ,6994.9
933.0921
River Rch & RM=DdlyFrk,Main      ,3311.8
1030.433
River Rch & RM=DdlyFrk,Main      ,234
1143.916
Boundary for River Rch & Prof#=DdlyFrk,Main      ,1
Up Type=0
Dn Type=3
Dn Slope=0.00841

--- DdlyFrk.g01 (geometry) ---

Geom Title=USGS 3m DEM
Program Version=4.00

River Reach=DdlyFrk     ,Main
Reach XY= 30
     1738423.586      397447.317     1738185.233      397262.647
     1737590.425      397112.335     1737517.416      397067.241
     1737483.059      396936.254     1737371.398      396884.718
     1736914.018      396891.161     1736175.340      396710.785
     1735612.742      396236.227     1735524.701      396100.946
     1735067.322      395954.928     1735063.027      395886.214
     1735005.049      395886.214     1734850.442      395656.450
     1734644.299      395173.303     1734444.598      395128.209
     1734165.447      394864.089     1734040.902      394743.838
     1733963.598      394509.780     1733637.205      394215.597
     1733437.504      394131.852     1733156.205      394159.767
     1733048.839      394099.642     1732911.410      393992.276
     1732578.576      393504.834     1732104.018      393270.776
     1731558.598      392813.396     1731191.406      392607.253
     1730970.231      392396.816     1730902.742      392416.880

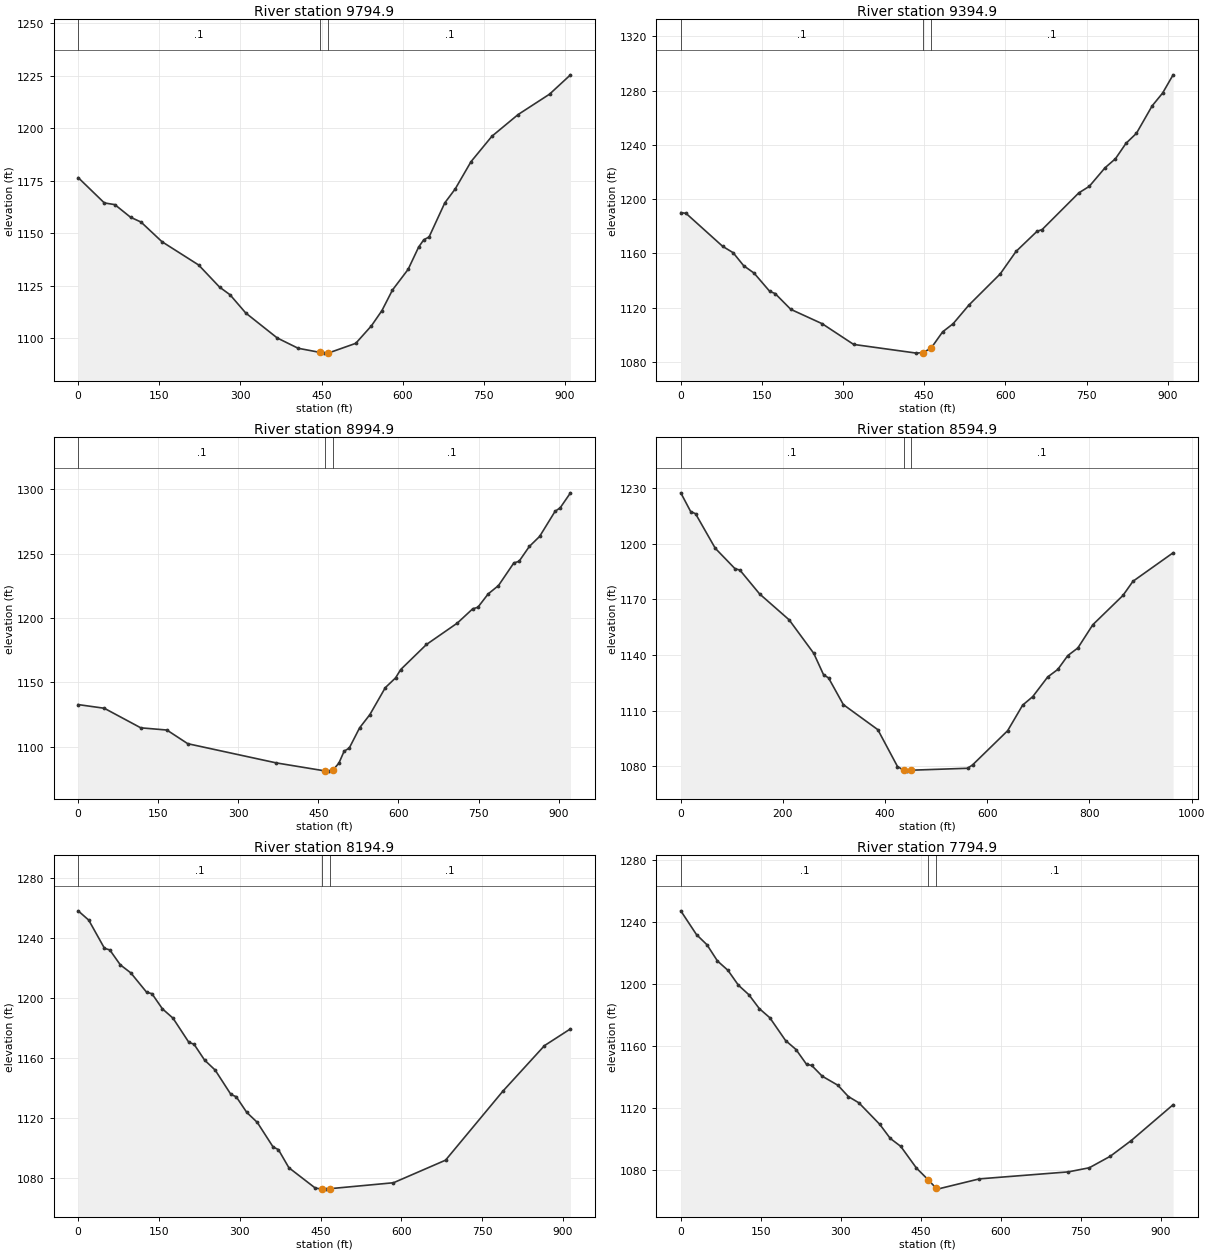
Type RM Length L Ch R = 1 ,9794.9,408.824,400,391.176
XS GIS Cut Line= 3
     1738720.532      397102.428     1738416.153      397440.627
     1738111.774      397778.826
#Sta/Elev= 30
       0 1176.48    48.4 1164.39    67.8 1163.58    96.8 1157.57   116.2 1155.27
   154.9 1145.90   222.7 1134.79   261.4 1124.24   280.7 1120.60   309.8 1111.89
   367.9 1100.00   406.6 1095.08   447.5 1093.08   455.0 1092.76   462.5 1092.81
   513.1 1097.43   542.1 1105.80   561.5 1113.06   580.9 1122.84   609.9 1132.71
   629.3 1143.32   638.9 1146.85   648.6 1148.14   677.7 1164.42   697.0 1171.09
   726.1 1184.06   764.8 1196.20   813.2 1206.54   871.3 1216.26   910.0 1225.48
#Mann= 3 , 0 , 0
       0     0.1       0   447.5   0.045       0   462.5     0.1       0
Bank Sta=   447.5,   462.5
Exp/Cntr=0.3,0.1

Type RM Length L Ch R = 1 ,9394.9,397.62,400,395.106
XS GIS Cut Line= 3
     1738236.644      396797.984     1738084.072      397226.641
     1737931.499      397655.297
#Sta/Elev= 30
       0 1190.10     9.7 1189.53    77.4 1165.25    96.8 1160.55   116.2 1151.00
   135.5 1145.51   164.6 1132.00   174.3 1130.51   203.3 1118.85   261.4 1108.25
   319.5 1093.01   435.6 1086.60   447.5 1086.98   462.5 1090.19   484.0 1102.27
   503.4 1108.26   532.4 1121.93   590.5 1144.98   619.6 1161.46   658.3 1176.24
   668.0 1177.64   735.7 1204.61   755.1 1209.44   784.1 1223.07   803.5 1229.80
   822.9 1241.11   842.2 1248.48   871.3 1268.72   890.6 1278.14   910.0 1291.55
#Mann= 3 , 0 , 0
       0     0.1       0   447.5   0.045       0   462.5     0.1       0
Bank Sta=   447.5,   462.5
Exp/Cntr=0.3,0.1

Type RM Length L Ch R = 1 ,8994.9,401.21,400,406.788
XS GIS Cut Line= 3
     1737896.086      396695.476     1737699.158      397121.396
     1737642.789      397570.825
#Sta/Elev= 30
       0 1132.65    48.9 1129.80   117.3 1114.57   166.2 1112.85   205.3 1102.22
   371.5 1087.25   461.7 1081.09   469.2 1080.88   476.7 1081.42   488.5 1087.17
   498.2 1096.41   507.8 1098.81   527.1 1114.50   546.3 1124.79   575.3 1145.81
   594.5 1153.41   604.2 1159.93   652.4 1179.41   710.2 1196.06   739.1 1207.19
   748.7 1208.34   768.0 1218.75   787.3 1225.25   816.2 1242.93   825.8 1244.07
   845.1 1255.68   864.4 1263.49   893.3 1283.01   902.9 1285.75   922.2 1297.41
#Mann= 3 , 0 , 0
       0     0.1       0   461.7   0.045       0   476.7     0.1       0
Bank Sta=   461.7,   476.7
Exp/Cntr=0.3,0.1

Type RM Length L Ch R = 1 ,8594.9,410.033,400,387.228
XS GIS Cut Line= 3
     1737606.437      396504.737     1737420.583      396907.419
     1737179.197      397368.167
#Sta/Elev= 30
       0 1227.49    19.3 1217.41    28.9 1216.21    67.5 1197.56   106.1 1186.56
   115.7 1185.79   154.3 1172.92   212.1 1158.94   260.3 1140.85   279.6 1129.23
   289.2 1127.61   318.2 1113.18   385.7 1099.66   424.2 1079.77     436 1077.86
   443.5 1077.28     451 1077.78   561.3 1078.82   571.1 1080.63   639.8 1099.10
   669.2 1112.91   688.9 1117.48   718.3 1128.13   737.9 1132.15   757.6 1139.66
   777.2 1143.74   806.6 1156.32   865.5 1172.10   885.1 1179.74   963.7 1195.13
#Mann= 3 , 0 , 0
       0     0.1       0     436   0.045       0     451     0.1       0
Bank Sta=     436,     451
Exp/Cntr=0.3,0.1

Type RM Length L Ch R = 1 ,8194.9,393.401,400,403.995
XS GIS Cut Line= 3
     1737023.127      396443.363     1737027.574      396903.160
     1737064.104      397356.095
#Sta/Elev= 30
       0 1258.24    19.6 1252.05    48.9 1233.18    58.7 1232.13    78.3 1222.14
    97.8 1216.77   127.2 1203.81   137.0 1202.89   156.5 1192.73   176.1 1186.53
   205.5 1170.40   215.2 1169.08   234.8 1158.49   254.4 1151.84   283.7 1135.52
   293.5 1134.03   313.1 1123.55   332.6 1116.89   362.0 1100.44   371.8 1098.70
   391.3 1086.59   440.3 1073.00   452.3 1072.32   459.8 1072.29   467.3 1072.58
   585.5 1076.55   682.2 1091.63   788.5 1137.68   865.9 1168.17   914.2 1179.38
#Mann= 3 , 0 , 0
       0     0.1       0   452.3   0.045       0   467.3     0.1       0
Bank Sta=   452.3,   467.3
Exp/Cntr=0.3,0.1

Type RM Length L Ch R = 1 ,7794.9,397.944,400,400.814
XS GIS Cut Line= 3
     1736765.723      396384.104     1736636.187      396837.477
     1736591.893      397287.207
#Sta/Elev= 30
       0 1247.22    29.5 1231.89    49.1 1225.38    68.8 1214.91    88.4 1208.92
   108.1 1199.31   127.7 1193.19   147.3 1184.23   167.0 1178.36   196.5 1163.68
   216.1 1157.89   235.8 1148.37   245.6 1147.61   265.2 1140.72   294.7 1134.85
   314.3 1127.58   334.0 1123.56   373.3 1109.64   392.9 1100.62   412.6 1095.48
   442.0 1081.51     464 1073.99     479 1068.52   481.3 1067.95   559.9 1074.55
   726.9 1079.06   766.2 1081.71   805.5 1089.11   844.8 1099.22   923.4 1122.33
#Mann= 3 , 0 , 0
       0     0.1       0     464   0.045       0     479     0.1       0
Bank Sta=     464,     479
Exp/Cntr=0.3,0.1

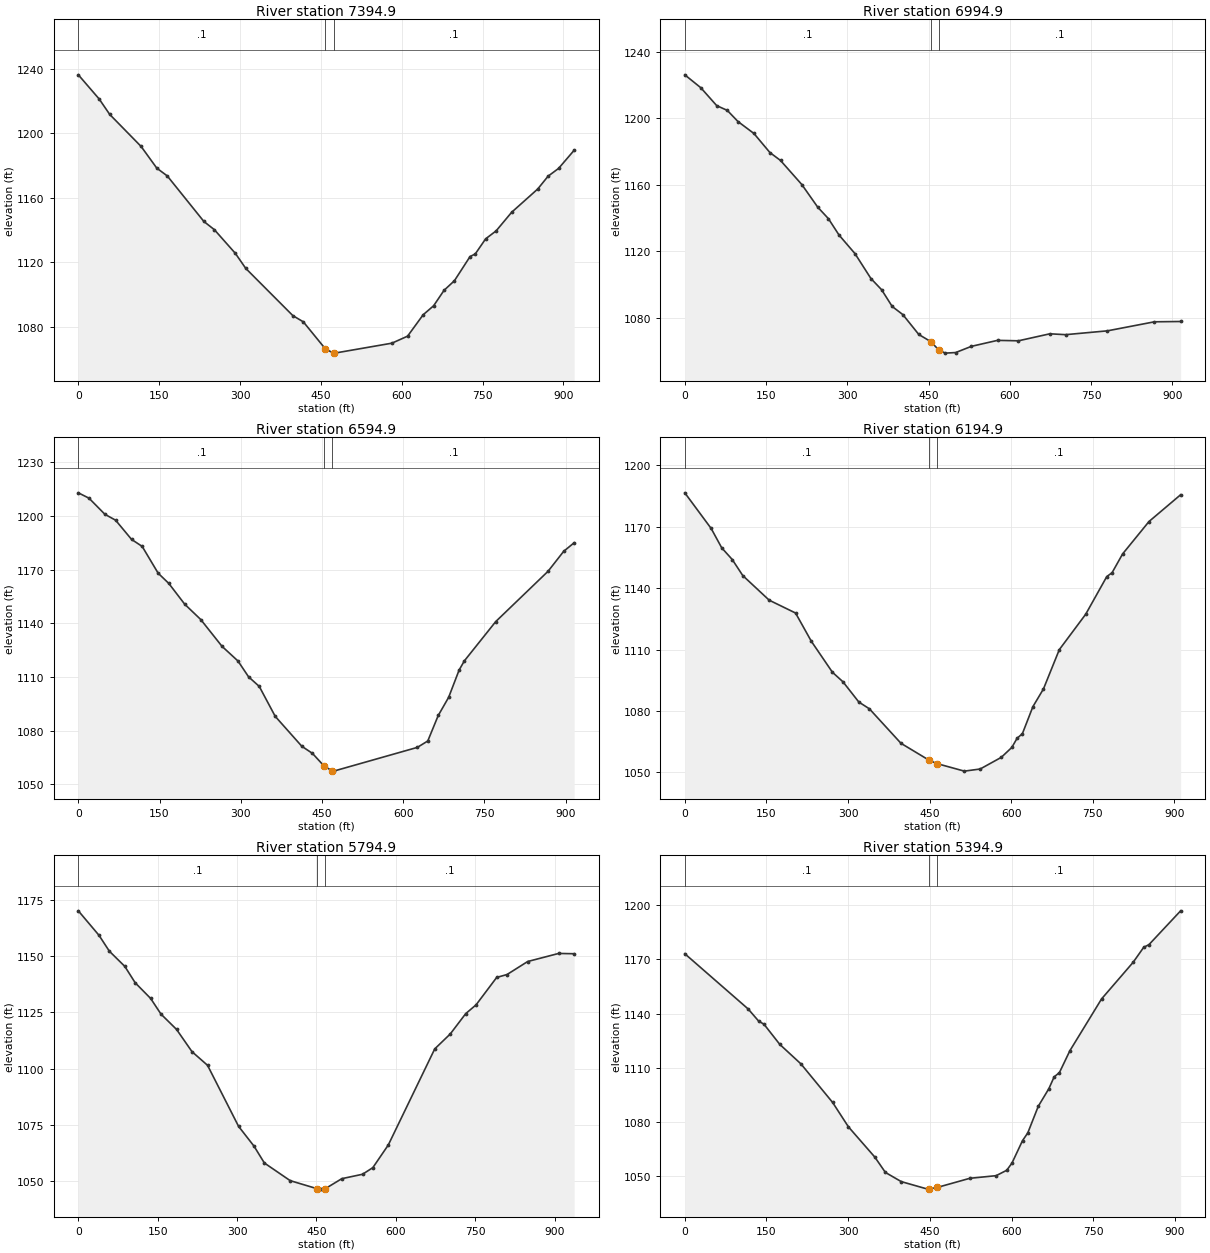
Type RM Length L Ch R = 1 ,7394.9,395.576,400,409.9
XS GIS Cut Line= 3
     1736430.104      396280.324     1736262.542      396715.033
     1736204.769      397165.283
#Sta/Elev= 30
       0 1236.16    38.8 1221.14    58.2 1211.65   116.5 1191.79   145.6 1178.36
   165.0 1173.55   232.9 1145.35   252.4 1140.25   291.2 1125.64   310.6 1116.29
   397.9 1087.06   417.4 1083.19   458.4 1066.40   473.4 1063.83   475.5 1063.82
   581.8 1069.99   610.8 1074.33   639.7 1087.58   659.1 1093.15   678.4 1102.70
   697.7 1108.66   726.7 1123.64   736.3 1125.22   755.6 1134.60   775.0 1139.51
   803.9 1151.06   852.2 1165.45   871.5 1173.41   890.9 1178.20   919.8 1189.45
#Mann= 3 , 0 , 0
       0     0.1       0   458.4   0.045       0   473.4     0.1       0
Bank Sta=   458.4,   473.4
Exp/Cntr=0.3,0.1

Type RM Length L Ch R = 1 ,6994.9,396.299,400,399.808
XS GIS Cut Line= 3
     1736194.269      396134.304     1735941.460      396520.328
     1735692.445      396899.780
#Sta/Elev= 30
       0 1226.25    29.5 1218.49    58.9 1207.70    78.5 1204.82    98.2 1198.11
   127.6 1190.93   157.1 1179.44   176.7 1174.67   216.0 1160.18   245.4 1146.54
   265.1 1139.63   284.7 1129.76   314.2 1118.55   343.6 1103.56   363.3 1096.82
   382.9 1086.72   402.5 1081.84   432.0 1069.85   453.9 1065.61   468.9 1060.54
   480.8 1058.63   500.1 1058.98   529.0 1062.71   577.3 1066.32   615.9 1066.05
   673.9 1070.27   702.9 1069.75   780.1 1072.05   867.0 1077.50   915.3 1077.68
#Mann= 3 , 0 , 0
       0     0.1       0   453.9   0.045       0   468.9     0.1       0
Bank Sta=   453.9,   468.9
Exp/Cntr=0.3,0.1

Type RM Length L Ch R = 1 ,6594.9,410.265,400,393.755
XS GIS Cut Line= 3
     1735955.604      395915.295     1735643.340      396255.552
     1735397.535      396637.036
#Sta/Elev= 30
       0 1213.04    19.7 1210.05    49.1 1201.03    68.8 1197.74    98.3 1187.00
   117.9 1183.08   147.4 1168.11   167.0 1162.41   196.5 1150.76   226.0 1142.22
   265.3 1127.23   294.8 1119.02   314.4 1110.16   334.1 1104.81   363.6 1088.06
   412.7 1071.34   432.3 1067.38   454.3 1060.13   469.3 1057.56   471.5 1057.45
   626.0 1070.72   645.3 1074.30   664.6 1088.55   683.9 1098.75   703.2 1113.99
   712.9 1119.11   770.8 1141.06   867.4 1169.18   896.3 1180.35   915.6 1185.13
#Mann= 3 , 0 , 0
       0     0.1       0   454.3   0.045       0   469.3     0.1       0
Bank Sta=   454.3,   469.3
Exp/Cntr=0.3,0.1

Type RM Length L Ch R = 1 ,6194.9,377.571,400,402.807
XS GIS Cut Line= 3
     1735466.566      395615.868     1735329.024      396050.215
     1735188.554      396483.876
#Sta/Elev= 30
       0 1186.64    48.5 1169.21    67.9 1159.75    87.2 1154.06   106.6 1146.20
   155.1 1134.19   203.6 1127.91   232.6 1114.10   271.4 1098.96   290.8 1094.29
   319.9 1084.42   339.3 1081.11   397.4 1064.25   448.1 1056.14   463.1 1054.37
   513.8 1050.66   542.9 1051.69   581.7 1057.38   601.1 1062.23   610.8 1066.72
   620.5 1068.93   639.9 1082.18   659.3 1090.84   688.4 1110.02   736.9 1127.31
   775.7 1145.73   785.4 1147.61   804.8 1156.80   853.3 1172.63   911.4 1185.70
#Mann= 3 , 0 , 0
       0     0.1       0   448.1   0.045       0   463.1     0.1       0
Bank Sta=   448.1,   463.1
Exp/Cntr=0.3,0.1

Type RM Length L Ch R = 1 ,5794.9,385.745,400,406.635
XS GIS Cut Line= 3
     1735317.931      395516.266     1735046.212      395886.214
     1734700.502      396216.384
#Sta/Elev= 30
       0 1170.14    39.1 1159.25    58.6 1152.22    87.9 1145.45   107.4 1138.20
   136.7 1131.21   156.3 1124.24   185.6 1117.47   214.9 1107.56   244.2 1101.52
   302.8 1074.43   332.1 1065.59   351.6 1058.13   400.4 1050.29   451.5 1046.69
   459.0 1046.52   466.5 1046.68   498.0 1051.17   537.1 1053.12   556.6 1056.06
   585.8 1066.12   673.6 1108.81   702.9 1115.43   732.2 1124.49   751.7 1128.37
   790.7 1140.56   810.2 1141.84   849.3 1147.63   907.8 1151.21   937.1 1151.08
#Mann= 3 , 0 , 0
       0     0.1       0   451.5   0.045       0   466.5     0.1       0
Bank Sta=   451.5,   466.5
Exp/Cntr=0.3,0.1

Type RM Length L Ch R = 1 ,5394.9,405.201,400,388.677
XS GIS Cut Line= 3
     1735254.233      395423.447     1734828.074      395584.766
     1734395.241      395724.671
#Sta/Elev= 30
       0 1173.07   116.3 1142.56   135.7 1135.81   145.4 1134.12   174.5 1122.95
   213.3 1112.18   271.5 1090.87   300.5 1077.40   349.0 1060.67   368.4 1052.20
   397.5 1047.13   446.0 1042.97   448.2 1043.07   463.2 1043.87   523.4 1048.95
   571.8 1050.41   591.2 1053.39   600.8 1057.33   620.2 1069.76   629.9 1074.04
   649.2 1088.78   668.6 1098.48   678.3 1104.99   688.0 1107.38   707.3 1119.51
   765.4 1148.09   823.4 1168.33   842.8 1176.61   852.5 1178.11   910.6 1196.78
#Mann= 3 , 0 , 0
       0     0.1       0   448.2   0.045       0   463.2     0.1       0
Bank Sta=   448.2,   463.2
Exp/Cntr=0.3,0.1

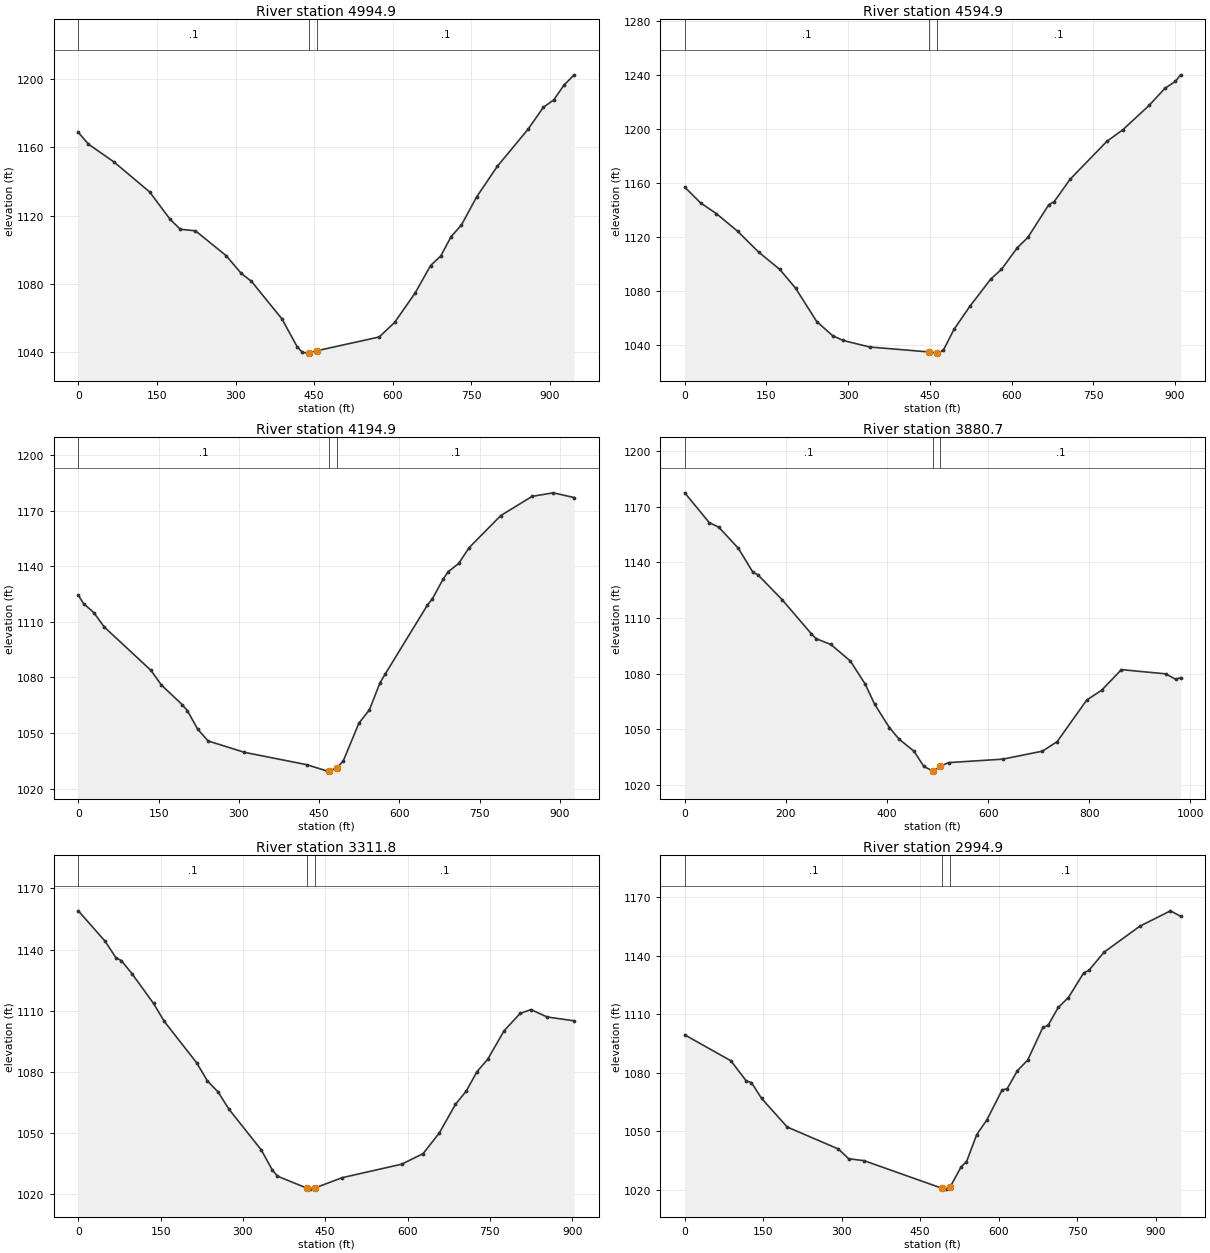
Type RM Length L Ch R = 1 ,4994.9,407.253,400,398.203
XS GIS Cut Line= 3
     1735046.054      394969.404     1734674.818      395218.741
     1734330.840      395580.534
#Sta/Elev= 30
       0 1168.83    19.4 1161.94    68.1 1151.52   136.1 1133.96   175.0 1118.01
   194.4 1112.11   223.6 1111.18   281.9 1096.70   311.1 1086.19   330.5 1081.57
   388.9 1059.46   418.0 1043.06   427.8 1040.00   437.5 1039.51   439.7 1039.70
   454.7 1040.87   574.4 1048.98   603.8 1057.55   643.0 1074.81   672.3 1090.82
   691.9 1096.48   711.5 1107.76   731.1 1114.53   760.4 1131.11   799.6 1148.90
   858.3 1170.67   887.7 1183.59   907.3 1187.84   926.8 1196.48   946.4 1202.58
#Mann= 3 , 0 , 0
       0     0.1       0   439.7   0.045       0   454.7     0.1       0
Bank Sta=   439.7,   454.7
Exp/Cntr=0.3,0.1

Type RM Length L Ch R = 1 ,4594.9,393.083,400,400.168
XS GIS Cut Line= 3
     1734653.625      394685.165     1734354.585      395028.812
     1734041.058      395358.417
#Sta/Elev= 30
       0 1157.03    29.1 1145.35    58.2 1137.37    96.9 1124.42   135.7 1108.90
   174.5 1096.07   203.5 1082.14   242.3 1057.43   271.4 1046.99   290.8 1043.43
   339.2 1038.60     448 1034.94     463 1034.09   465.2 1034.05   474.9 1036.36
   494.3 1051.68   523.3 1068.69   562.0 1089.04   581.4 1096.10   610.4 1112.10
   629.8 1119.74   668.5 1144.15   678.2 1146.30   707.2 1162.78   774.9 1190.97
   804.0 1199.49   852.4 1217.58   881.4 1230.20   900.8 1235.50   910.4 1240.29
#Mann= 3 , 0 , 0
       0     0.1       0     448   0.045       0     463     0.1       0
Bank Sta=     448,     463
Exp/Cntr=0.3,0.1

Type RM Length L Ch R = 1 ,4194.9,314.989,314.159,319.08
XS GIS Cut Line= 3
     1734462.863      394510.954     1734058.208      394760.547
     1733744.672      395085.280
#Sta/Elev= 30
       0 1124.40     9.7 1119.94    29.1 1114.97    48.5 1107.25   135.8 1083.82
   155.2 1075.93   194.1 1065.33   203.8 1062.11   223.2 1052.02   242.6 1045.70
   310.5 1039.55   426.9 1032.88   465.7 1029.40   467.9 1029.50   482.9 1030.99
   495.1 1034.88   524.5 1055.32   544.1 1062.51   563.8 1077.08   573.6 1081.85
   652.1 1118.90   661.9 1122.54   681.5 1132.95   691.3 1137.06   710.9 1141.57
   730.6 1150.14   789.5 1167.41   848.3 1177.81   887.6 1179.72   926.8 1177.17
#Mann= 3 , 0 , 0
       0     0.1       0   467.9   0.045       0   482.9     0.1       0
Bank Sta=   467.9,   482.9
Exp/Cntr=0.3,0.1

Type RM Length L Ch R = 1 ,3880.7,585.376,568.904,552.431
XS GIS Cut Line= 3
     1734297.080      394135.844     1734009.482      394434.094
     1733537.144      394747.021
#Sta/Elev= 30
       0 1177.55    48.2 1161.53    67.4 1158.96   106.0 1147.60   134.9 1134.59
   144.5 1133.35   192.7 1119.82   250.5 1101.40   260.2 1098.76   289.1 1095.67
   327.6 1086.73   356.5 1074.48   375.8 1063.33   404.7 1050.84   424.1 1044.53
   453.4 1038.08   472.9 1029.86   490.7 1027.33   492.5 1027.31   505.7 1029.98
   521.8 1031.91   629.2 1033.78   707.4 1038.09   736.7 1043.24   795.3 1065.73
   824.6 1070.96   863.7 1082.10   951.6 1079.82   971.1 1076.90   980.9 1077.79
#Mann= 3 , 0 , 0
       0     0.1       0   490.7   0.045       0   505.7     0.1       0
Bank Sta=   490.7,   505.7
Exp/Cntr=0.3,0.1

Type RM Length L Ch R = 1 ,3311.8,316.122,316.937,307.411
XS GIS Cut Line= 3
     1733626.018      393752.381     1733551.456      393933.461
     1733365.329      394616.375
#Sta/Elev= 30
       0 1159.02    49.0 1144.06    68.5 1136.03    78.3 1134.65    97.9 1128.19
   137.1 1113.61   156.7 1104.81   215.5 1084.62   235.2 1075.69   254.8 1070.23
   274.5 1061.80   333.5 1041.83   353.1 1032.22   363.0 1028.97   415.9 1023.20
   421.9 1022.63   430.9 1023.16   480.9 1028.25   589.1 1034.84   628.4 1040.03
   657.9 1050.15   687.4 1064.20   707.0 1070.68   726.7 1080.22   746.4 1086.38
   775.9 1100.22   805.3 1108.75   825.0 1110.61   854.5 1107.00   903.7 1105.11
#Mann= 3 , 0 , 0
       0     0.1       0   415.9   0.045       0   430.9     0.1       0
Bank Sta=   415.9,   430.9
Exp/Cntr=0.3,0.1

Type RM Length L Ch R = 1 ,2994.9,501.722,513.897,536.414
XS GIS Cut Line= 3
     1733315.227      393671.417     1733184.096      394153.240
     1733250.715      394596.827
#Sta/Elev= 30
       0 1099.51    88.1 1086.23   117.5 1075.90   127.3 1075.08   146.9 1066.91
   195.8 1052.27   293.7 1040.99   313.3 1035.99   342.7 1035.02   491.8 1020.85
   499.3 1020.42   506.8 1021.28   528.6 1032.02   538.4 1034.31   557.9 1048.29
   577.4 1055.88   606.6 1071.24   616.4 1071.95   635.9 1081.17   655.4 1086.55
   684.6 1103.37   694.4 1104.35   713.9 1113.56   733.4 1118.66   762.6 1131.29
   772.4 1132.56   801.6 1141.93   869.9 1155.22   928.4 1163.11   947.9 1160.31
#Mann= 3 , 0 , 0
       0     0.1       0   491.8   0.045       0   506.8     0.1       0
Bank Sta=   491.8,   506.8
Exp/Cntr=0.3,0.1

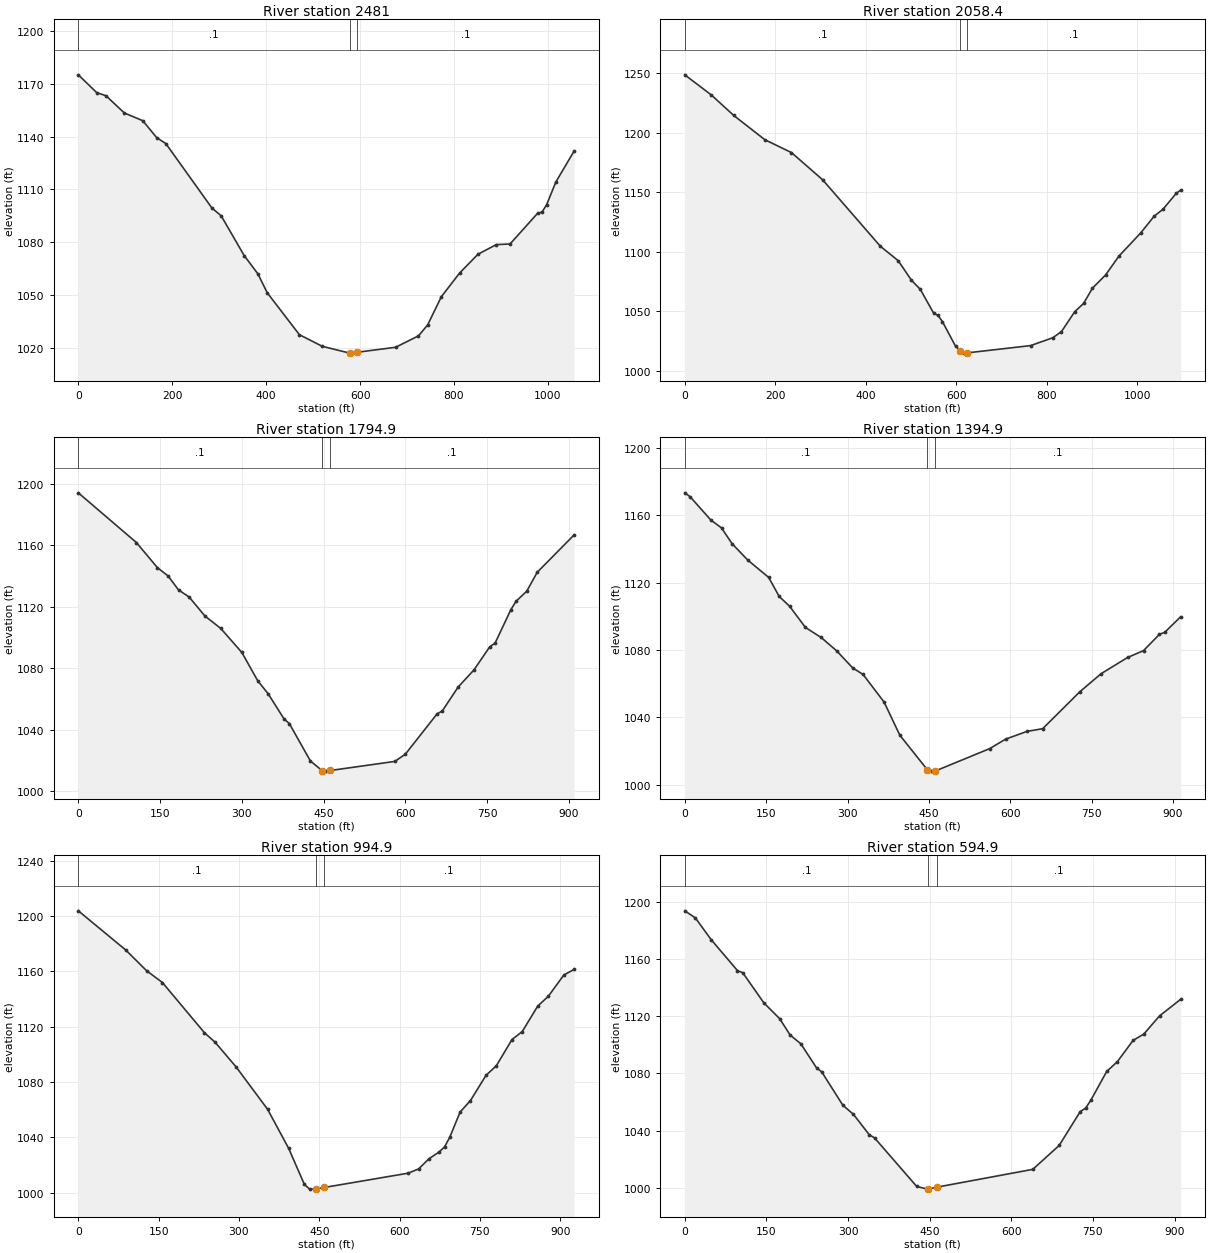
Type RM Length L Ch R = 1 ,2481,429.02,422.563,416.106
XS GIS Cut Line= 3
     1733263.858      393443.480     1732912.350      393741.729
     1732482.798      394153.199
#Sta/Elev= 30
       0 1174.97    39.2 1164.88    58.8 1163.14    98.1 1153.33   137.3 1148.97
   166.7 1139.42   186.4 1135.99   284.4 1099.52   304.1 1095.10   353.1 1072.58
   382.5 1062.13   402.1 1051.53   470.7 1027.72   519.5 1021.12   578.0 1017.27
   578.6 1017.28   593.6 1017.76   675.5 1020.58   724.3 1027.05   743.8 1033.24
   773.0 1049.24   812.0 1062.68   851.0 1073.31   890.0 1078.75   919.3 1079.12
   977.8 1096.45   987.6 1097.26   997.3 1101.43  1016.8 1114.23  1055.8 1131.83
#Mann= 3 , 0 , 0
       0     0.1       0   578.6   0.045       0   593.6     0.1       0
Bank Sta=   578.6,   593.6
Exp/Cntr=0.3,0.1

Type RM Length L Ch R = 1 ,2058.4,262.556,263.54,264.524
XS GIS Cut Line= 3
     1733050.823      393145.230     1732624.752      393390.221
     1732322.596      393914.161
#Sta/Elev= 30
       0 1248.79    59.0 1231.75   108.1 1214.68   176.9 1194.24   235.9 1183.42
   304.7 1160.58   432.5 1104.61   471.8 1092.56   501.2 1076.05   520.7 1068.44
   550.0 1048.54   559.8 1046.50   569.5 1041.37   598.8 1020.51   609.2 1016.93
   618.3 1014.79   624.2 1015.00   764.6 1021.12   813.4 1027.67   832.9 1032.92
   862.2 1049.66   881.7 1056.52   901.2 1069.33   930.5 1080.58   959.7 1096.26
  1008.5 1116.05  1037.8 1129.94  1057.3 1135.77  1086.6 1149.14  1096.3 1151.84
#Mann= 3 , 0 , 0
       0     0.1       0   609.2   0.045       0   624.2     0.1       0
Bank Sta=   609.2,   624.2
Exp/Cntr=0.3,0.1

Type RM Length L Ch R = 1 ,1794.9,401.449,400,400.797
XS GIS Cut Line= 3
     1732568.848      393004.723     1732324.260      393388.391
     1732079.671      393772.060
#Sta/Elev= 30
       0 1194.28   106.5 1161.92   145.2 1145.52   164.6 1140.18   183.9 1131.02
   203.3 1126.44   232.3 1114.05   261.4 1105.95   300.1 1090.31   329.1 1071.95
   348.5 1063.33   377.6 1046.97   387.2 1044.02   426.0 1019.57   447.5 1013.31
   455.0 1013.00   462.5 1013.41   580.9 1019.33   600.2 1024.04   658.3 1050.25
   668.0 1052.22   697.0 1067.74   726.1 1078.93   755.1 1093.99   764.8 1096.33
   793.8 1118.13   803.5 1123.70   822.9 1130.18   842.2 1142.53   910.0 1166.90
#Mann= 3 , 0 , 0
       0     0.1       0   447.5   0.045       0   462.5     0.1       0
Bank Sta=   447.5,   462.5
Exp/Cntr=0.3,0.1

Type RM Length L Ch R = 1 ,1394.9,396.155,400,400.862
XS GIS Cut Line= 3
     1732209.204      392774.148     1731998.714      393176.897
     1731746.540      393561.239
#Sta/Elev= 30
       0 1173.27     9.7 1170.99    48.3 1157.01    67.7 1152.46    87.0 1143.13
   116.0 1133.37   154.7 1123.02   174.0 1111.75   193.4 1105.86   222.4 1093.32
   251.4 1087.37   280.4 1079.33   309.4 1069.33   328.7 1065.42   367.4 1049.03
   396.4 1029.37   446.9 1008.95   454.4 1008.02   461.9 1008.11   562.0 1021.37
   591.4 1027.00   630.5 1031.57   659.8 1033.23   728.3 1055.15   767.4 1065.84
   816.3 1075.50   845.7 1079.57   875.0 1089.25   884.8 1090.45   914.1 1099.66
#Mann= 3 , 0 , 0
       0     0.1       0   446.9   0.045       0   461.9     0.1       0
Bank Sta=   446.9,   461.9
Exp/Cntr=0.3,0.1

Type RM Length L Ch R = 1 ,994.9,400.667,400,400.634
XS GIS Cut Line= 3
     1731978.537      392559.190     1731704.859      392918.391
     1731429.884      393304.941
#Sta/Elev= 30
       0 1203.87    88.4 1175.56   127.6 1160.50   157.1 1151.97   235.6 1115.62
   255.2 1108.88   294.5 1091.00   353.4 1060.30   392.7 1032.08   422.1 1005.96
   431.9 1002.52   441.8 1002.50   444.1 1002.64   459.1 1003.69   616.2 1014.05
   635.5 1017.12   654.9 1024.50   674.2 1029.48   683.9 1033.04   693.6 1040.00
   713.0 1058.27   732.3 1066.55   761.4 1084.84   780.7 1091.77   809.8 1110.68
   829.1 1116.55   858.2 1135.07   877.6 1141.96   906.6 1157.37   926.0 1161.52
#Mann= 3 , 0 , 0
       0     0.1       0   444.1   0.045       0   459.1     0.1       0
Bank Sta=   444.1,   459.1
Exp/Cntr=0.3,0.1

Type RM Length L Ch R = 1 ,594.9,364.244,360.883,356.957
XS GIS Cut Line= 3
     1731636.963      392349.055     1731375.132      392721.397
     1731103.617      393087.753
#Sta/Elev= 30
       0 1193.82    19.4 1188.87    48.4 1173.66    96.8 1151.97   106.5 1150.50
   145.3 1129.37   174.3 1118.34   193.7 1106.82   213.1 1100.79   242.1 1083.88
   251.8 1080.97   290.5 1057.69   309.9 1051.33   339.0 1037.07   348.7 1034.84
   426.1 1000.90   445.5  998.97   447.7  999.12   462.7 1000.31   639.5 1012.81
   688.0 1029.56   726.8 1053.31   736.5 1055.61   746.3 1061.31   775.4 1081.38
   794.8 1088.15   823.9 1103.13   843.3 1107.42   872.4 1120.24   911.2 1131.86
#Mann= 3 , 0 , 0
       0     0.1       0   447.7   0.045       0   462.7     0.1       0
Bank Sta=   447.7,   462.7
Exp/Cntr=0.3,0.1

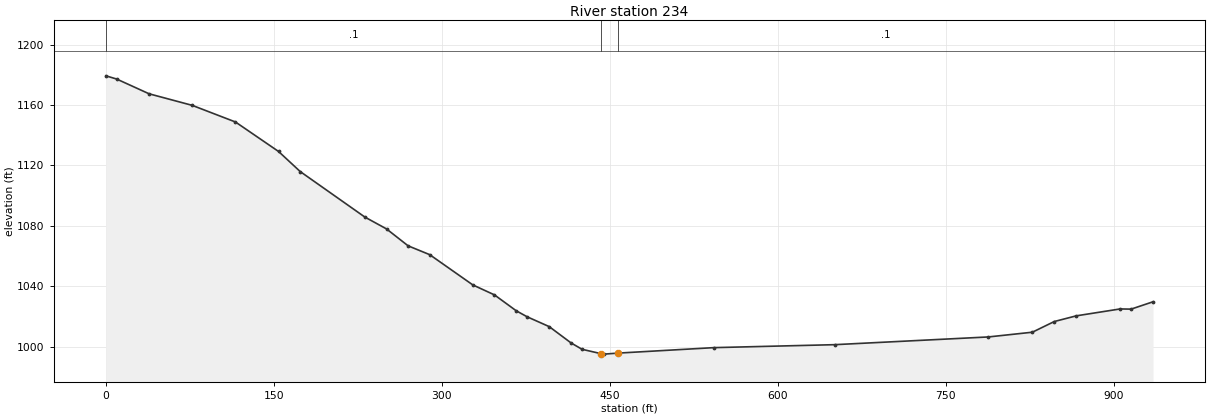
Type RM Length L Ch R = 1 ,234,252.971,233.985,213.656
XS GIS Cut Line= 3
     1731333.711      392125.788     1731133.505      392420.910
     1730875.100      392938.629
#Sta/Elev= 30
       0 1179.29     9.6 1177.17    38.6 1167.40    77.1 1159.76   115.7 1148.77
   154.2 1129.27   173.5 1116.01   231.3 1085.88   250.6 1078.07   269.9 1066.87
   289.2 1061.03   327.7 1041.02   347.0 1034.44   366.4 1023.96   376.2 1019.95
   395.9 1013.46   415.5 1002.63   425.3  998.44     442  995.60   444.9  995.26
     457  995.92   543.0  999.55   650.8 1001.51   788.1 1006.62   827.4 1009.75
   847.0 1016.82   866.6 1020.57   905.8 1025.14   915.6 1025.02   935.2 1029.88
#Mann= 3 , 0 , 0
       0     0.1       0     442   0.045       0     457     0.1       0
Bank Sta=     442,     457
Exp/Cntr=0.3,0.1